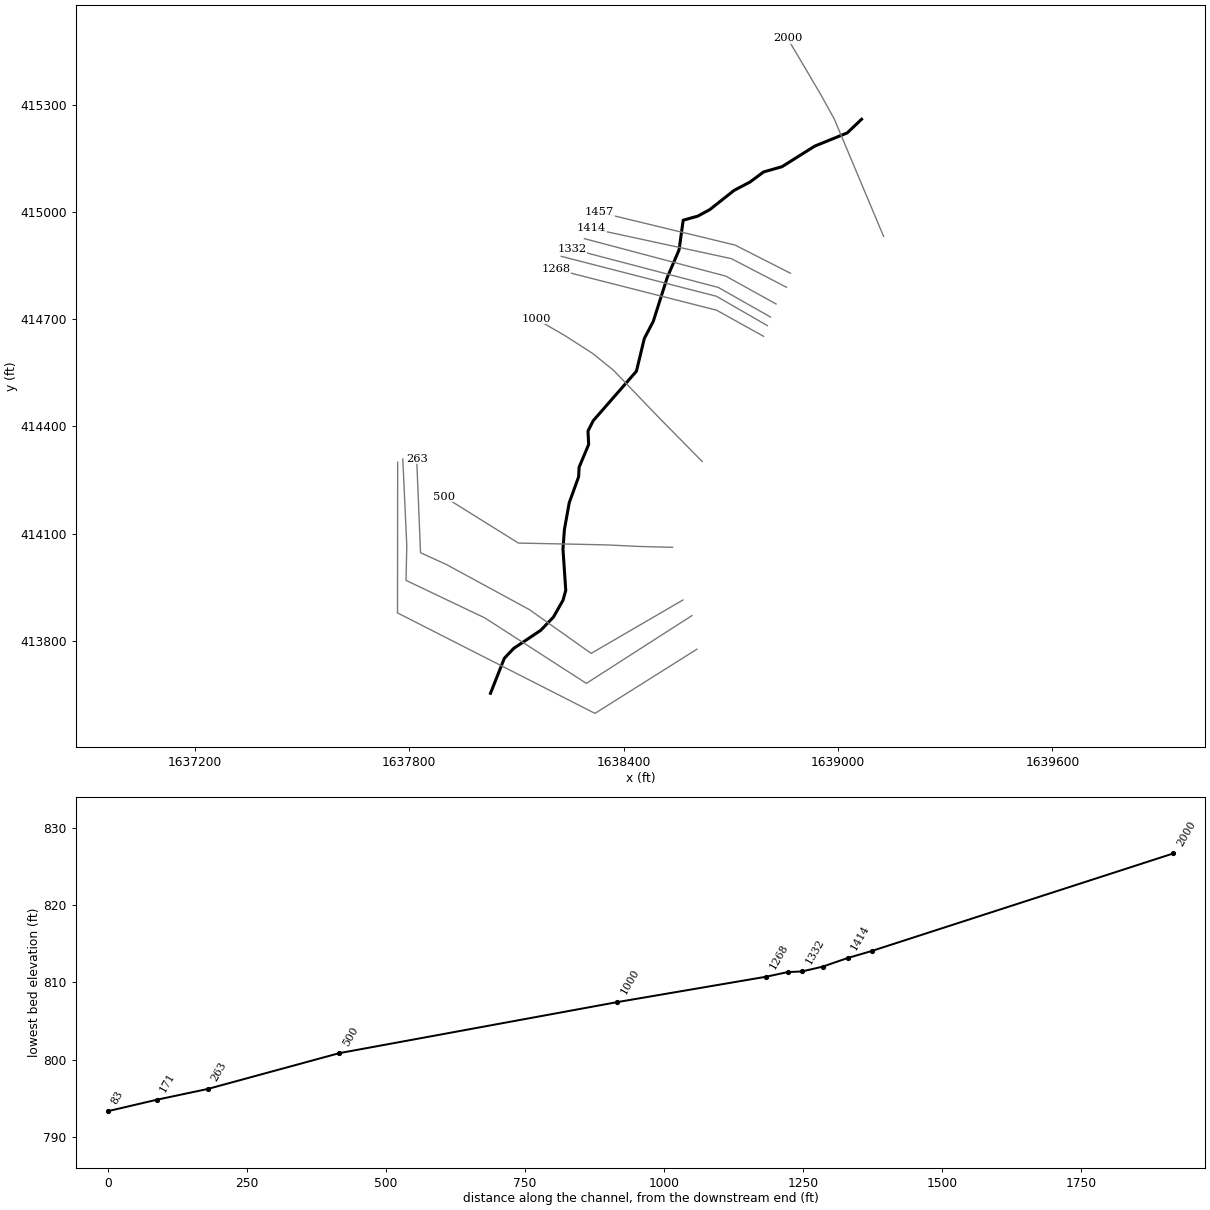
--- HARTLEYRN.prj (project) ---

Proj Title=HARTLEYRN
Current Plan=p01
Default Exp/Contr=0,0
English Units
Geom File=g01
Flow File=f01
Plan File=p01
BEGIN DESCRIPTION:
---------- MODELED AS PART OF WVEMD CTP PROGRAM, 2023----------
Stream Name: Hartley Run
Flood Zone:  AFH
Wetzel County, WV
HEC-RAS Version: RAS 6.3
Vertical Datum: NAVD88
Projection: NAD 1983 StatePlane West Virginia S FIPS 4702 (US Feet)
Terrain: 1-meter West Virginia FEMA R3 South Central (collected 2018-2020)
Land Use: 2019 NLCD
Hydrologic Method:
WV SIR2010-5033 regression equations
Additional Model Notes:
Leveraged XS
END DESCRIPTION:
DSS Export Rating Curves= 0
DSS Export Rating Curve Sorted= 0
DSS Export Volume Flow Curves= 0
DXF OffsetX= 0
DXF OffsetY= 0
DXF ScaleX= 0
DXF ScaleY= 0

--- HARTLEYRN.p01 (plan) ---

Plan Title=Floodplain
Program Version=6.30
Short Identifier=Floodplain
Geom File=g01
Flow File=f01
Subcritical Flow
K Sum by GR= 0
Std Step Tol= 0.01
Critical Tol= 0.01
Num of Std Step Trials= 20
Max Error Tol= 0.3
Flow Tol Ratio= 0.001
Split Flow NTrial= 30
Split Flow Tol= 0.02
Split Flow Ratio= 0.02
Log Output Level= 0
Friction Slope Method= 1
Unsteady Friction Slope Method= 2
Unsteady Bridges Friction Slope Method= 1
Parabolic Critical Depth
Global Vel Dist= 0 , 0 , 0
Global Log Level= 0
CheckData=True
Encroach Param=-1 ,0,0, 0
Mapping Interval=1HOUR
Computation Time Step Use Courant=        0
Computation Time Step Use Time Series=    0
Computation Time Step Count To Double=0
Computation Time Step Max Doubling=0
Computation Time Step Max Halving=0
Computation Time Step Residence Courant=0
Run HTab= 0
Run UNet= 0
Run Sediment= 0
Run PostProcess= 0
Run WQNet= 0
Run RASMapper= 0
UNET Theta= 0
UNET Theta Warmup= 0
UNET ZTol= 0
UNET ZSATol= 0
UNET MxIter= 0
UNET Max Iter WO Improvement= 0
UNET MaxInSteps= 0
UNET DtIC= 0
UNET DtMin= 0
UNET MaxCRTS= 0
UNET WFStab= 0
UNET SFStab= 0
UNET WFX= 1
UNET SFX= 1
UNET Gravity=32.17405
UNET 1D Methodology=Finite Difference
UNET DSS MLevel= 1
UNET Pardiso=0
UNET DZMax Abort= 0
UNET Use Existing IB Tables= 0
UNET Froude Reduction=False
UNET Froude Limit= 0
UNET Froude Power= 0
UNET D1 Cores= 0
UNET WindReference=Eulerian
UNET WindDragFormulation=Hsu (1988)
UNET D2 Coriolis=0
UNET D2 Cores= 0
UNET D2 Theta= 1
UNET D2 Theta Warmup= 1
UNET D2 Z Tol= 0.01
UNET D2 Volume Tol= 0.01
UNET D2 Max Iterations= 20
UNET D2 Equation= 0
UNET D2 RampUpFraction=0.1
UNET D2 TimeSlices= 1
UNET D2 Turbulence Formulation=Non-Conservative (original)
UNET D2 Eddy Viscosity=0.3
UNET D2 Transverse Eddy Viscosity=0.1
UNET D2 Smagorinsky Mixing=0
UNET D2 BCVolumeCheck=0
UNET D2 Cores=0
UNET D2 SolverType=PARDISO (Direct)
UNET D2 Minimum Iterations= 3
UNET D2 Maximum Iterations= 30
UNET D2 Restart Number= 10
UNET D2 Relaxation Coeff=1.3
UNET D2 SOR Precondition Iterations= 10
UNET D2 ILUT Maximum Fill= 8
UNET D2 ILUT Tolerance=1E-08
UNET D2 Convergence Tolerance=0.00001
UNET D1D2 MaxIter= 0
UNET D1D2 ZTol=0.01
UNET D1D2 QTol=0.1
UNET D1D2 MinQTol=1
Write IC File= 0
Write IC File at Fixed DateTime=0
Write IC File at Sim End=0
Echo Input=False
Echo Parameters=False
Echo Output=False
Write Detailed= 0
HDF Write Warmup=0
HDF Write Time Slices=0
HDF Flush=0
HDF Compression= 1
HDF Chunk Size= 1
HDF Spatial Parts= 1
HDF Use Max Rows=0
HDF Fixed Rows= 1
Calibration Method= 0
Calibration Iterations= 20
Calibration Max Change=0.05
Calibration Tolerance=0.2
Calibration Maximum=1.5
Calibration Minimum=0.5
Calibration Optimization Method= 1
WQ AD Non Conservative
WQ ULTIMATE=-1
WQ Max Comp Step=1HOUR
WQ Output Interval=15MIN
WQ Output Selected Increments= 0
WQ Output face flow=0
WQ Output face velocity=0
WQ Output face area=0
WQ Output face dispersion=0
WQ Output cell volume=0
WQ Output cell surface area=0
WQ Output cell continuity=0
WQ Output cumulative cell continuity=0
WQ Output face conc=0
WQ Output face dconc_dx=0
WQ Output face courant=0
WQ Output face peclet=0
WQ Output face adv mass=0
WQ Output face disp mass=0
WQ Output cell mass=0
WQ Output cell source sink temp=0
WQ Output nsm pathways=0
WQ Output nsm derived pathways=0
WQ Create Restart=0
WQ Fixed Restart=0
WQ System Summary=0
WQ Write To DSS=0
Sorting and Armoring Iterations= 10
XS Update Threshold= 0.02
Bed Roughness Predictor= 0
Hydraulics Update Threshold= 0.02
Energy Slope Method= 1
Volume Change Method= 1
Sediment Retention Method= 0
Sediment TS Multiplier= 1
Warm Up Method= 0
XS Weighting Method= 0
Number of US Weighted Cross Sections= 1
Number of DS Weighted Cross Sections= 1
Upstream XS Weight=0
Main XS Weight=1
Downstream XS Weight=0
Number of DS XS's Weighted with US Boundary= 1
Upstream Boundary Weight= 1
Weight of XSs Associated with US Boundary= 0
Number of US XS's Weighted with DS Boundary= 1
Downstream Boundary Weight= 0.5
Weight of XSs Associated with DS Boundary= 0.5
Percentile Method= 0
Sediment Output Level= 3
Mass or Volume Output= 0
Output Increment Type= 1
Profile and TS Output Increment= 1
Transport Output Increment 1
XS Output Flag= 0
XS Output Increment= 10
Read HDF5 Sediment Hotstart= 0
Sediment Hotstart Type= 0
Write Gradation File= 0
Read Gradation Hotstart= 0
Write HDF5 File= 1
Write Binary Output= 1
Write DSS Sediment File= 0
DSS Sediment Output Type= 1
SV Curve= 0
Specific Gage Flag= 0
Subcell Erosion Methods= 0
Subcell Deposition Methods= 0
Advection Scheme= 1
Matrix Solver= 0
Implicit Weighting Factor= 1
Maximum Outer Loop Convergence Iterations= 5
Convergence Maximum Absolute= 0.001
Convergence RMSE= 0.0001
Grain Fractions Max Abs Error= 0.001
Max Subgrid Regions= 1
Max Subgrid Length Scale= 3.402823E+38
Initial Layer Thickness= 3.402823E+38
Min Layer Thickness= 3.402823E+38
Max Layer Thickness= 3.402823E+38
Number of Layers= 5

--- HARTLEYRN.f01 (steady flow) ---

Flow Title=Flow
Program Version=4.00
Number of Profiles=1
Profile Names=F01pct
River Rch & RM=HARTLEYRN,Main,2000
     679
Boundary for River Rch & Prof#=HARTLEYRN,Main      ,1
Up Type=0
Dn Type=3
Dn Slope=0.011731

--- HARTLEYRN.g01 (geometry) ---

Geom Title=Geometry
Program Version=6.31

River Reach=HARTLEYRN       ,Main
Reach XY= 30
     1639066.058      415259.582     1639025.949      415221.316
     1638935.126      415184.434     1638843.381      415126.805
     1638791.745      415112.052     1638753.941       415083.93
     1638709.221      415060.417     1638640.989      415006.476
     1638607.795      414988.496     1638566.763      414976.971
     1638555.237      414893.985     1638522.043      414816.532
     1638482.855      414693.437      1638457.96      414645.951
     1638435.831      414554.206     1638315.041      414415.898
     1638300.288      414386.853     1638302.132      414349.048
     1638275.392      414285.426     1638274.009      414258.686
      1638247.73      414185.844     1638234.361      414111.618
     1638230.211      414056.756     1638238.049      413940.576
     1638230.211      413912.914     1638203.471      413865.889
1638167.84290806413828.8840766151638092.06795403413778.213107261
     1638066.085      413750.632      1638027.39      413652.738

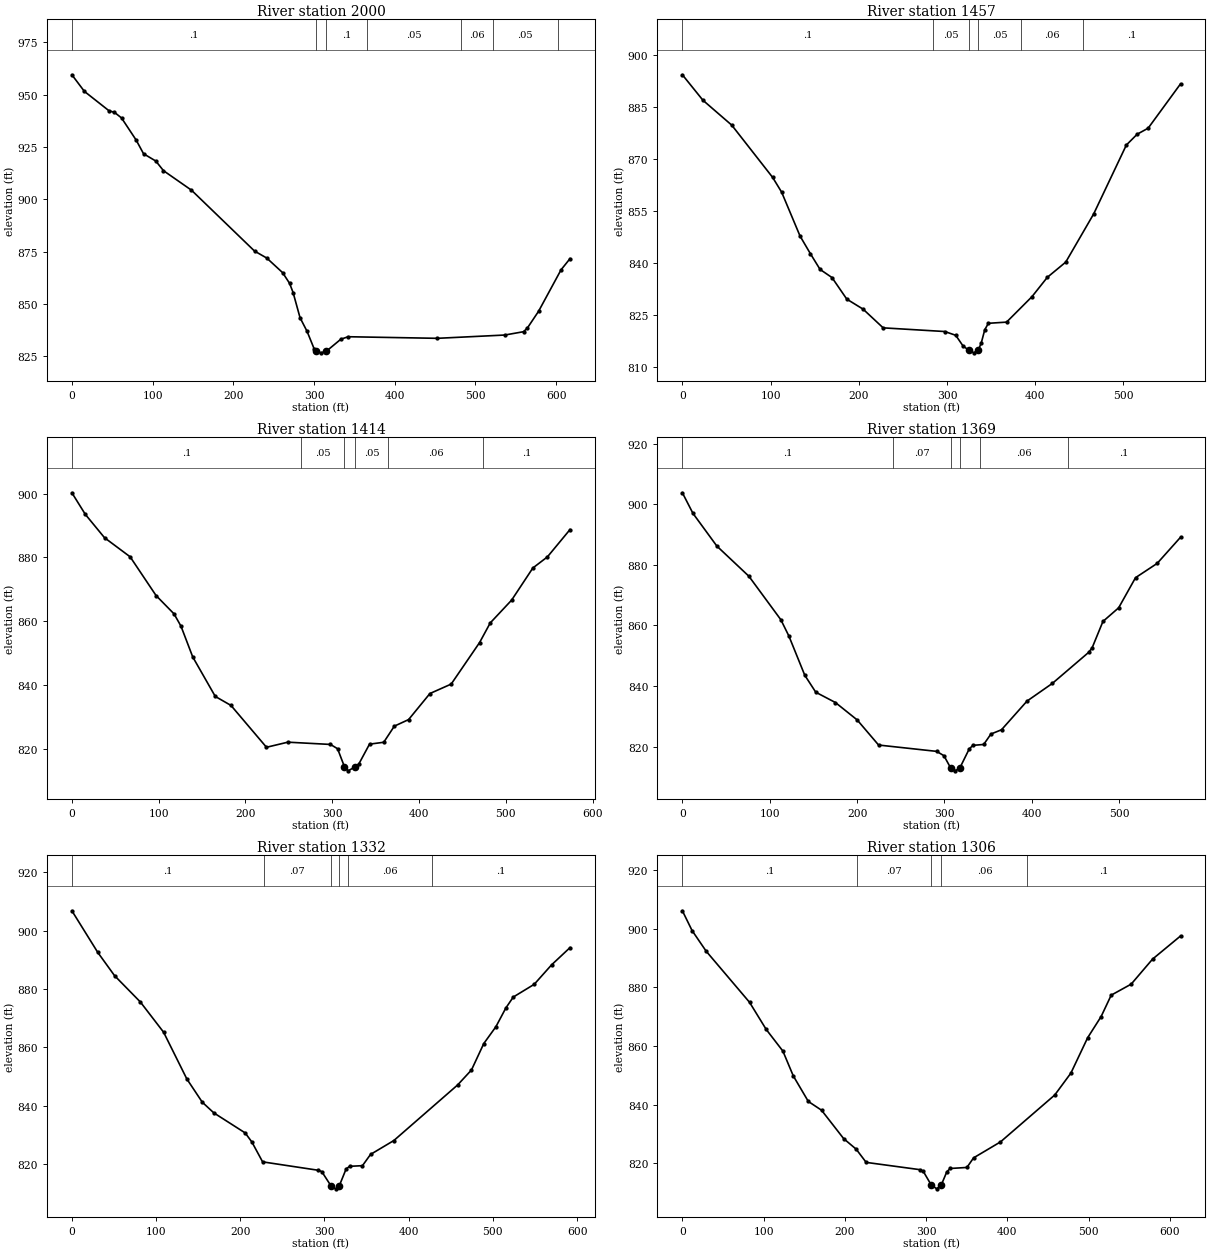
Type RM Length L Ch R = 1 ,2000    ,539.4,542.8,548.4
BEGIN DESCRIPTION:
Structure 3 XS 4
END DESCRIPTION:
XS GIS Cut Line= 6
1639127.68093017414931.8738463371639091.35652776415018.300838843
1638989.64905401415260.2964178321638952.84335335415326.825156167
1638907.54849643415403.9565635921638858.79367268  415486.0859925
#Sta/Elev= 30
       0  959.43    15.5   951.5      46  942.25    52.8  941.47    61.5  938.83
    79.6  928.28    88.8  921.73     104  918.24   113.5  913.65   148.2  904.33
   226.3  875.28   241.5  871.93   261.1  864.97   269.7  859.89   274.1  855.47
   282.7  843.45   291.4  836.95   300.1  828.67   302.6  827.47   308.6  826.69
  315.36 827.479   333.2  833.18   342.3  834.38   452.8  833.62   536.4  835.19
   559.6  836.78   564.3   838.5   578.2   846.5   606.1  866.33   617.2  871.66
#Mann= 7 ,-1,0
       0      .1       0   302.6    .045       0  315.36      .1       0
  366.25     .05       0  482.28     .06       0  521.73     .05       0
  601.73      .1       0
Bank Sta=302.6,315.36
XS Rating Curve= 0 ,0
Exp/Cntr(USF)=0,0
Exp/Cntr=0.3,0.1

Type RM Length L Ch R = 1 ,1457    ,43.7,43.3,43.7
BEGIN DESCRIPTION:
Structure 3 XS 3
END DESCRIPTION:
XS GIS Cut Line= 3
1638867.26292905414828.3784505411638711.82700568414907.413665817
1638332.45797235414999.094515538
#Sta/Elev= 30
       0  894.16    23.3  886.82      56  879.64   102.3   864.6   112.5  860.35
   133.4  847.69   145.2  842.58   156.1  838.08   169.6  835.74   186.4  829.52
   204.9  826.63   227.6  821.25   297.5  820.19   309.9   819.1   318.1  816.05
   324.4  814.85   330.5  814.05   335.3  814.82   338.7  816.77   342.8  820.71
   346.9  822.56   367.5   822.9   396.3  830.23   413.7   835.8   434.6  840.19
   466.3  854.09   503.3  873.92   515.6  877.04     528  878.77   564.7  891.53
#Mann= 6 ,-1,0
       0      .1       0  284.38     .05       0   324.4    .045       0
   335.3     .05       0  384.38     .06       0  454.38      .1       0
Bank Sta=324.4,335.3
XS Rating Curve= 0 ,0
Exp/Cntr(USF)=0,0
Exp/Cntr=0.3,0.1

Type RM Length L Ch R = 1 ,1414    ,45.8,44.6,44.7
BEGIN DESCRIPTION:
Structure 3 XS 2
END DESCRIPTION:
XS GIS Cut Line= 3
1638855.67109748414789.3877443381638701.28897697414869.476762485
1638310.32811207414953.780992113
#Sta/Elev= 30
       0  900.25    15.5  893.48    37.6  886.17    67.1  880.19      97  868.05
   117.7  862.31   125.7  858.46   139.2  848.84   165.2  836.45   183.3  833.63
   224.2  820.52   248.8  822.12   297.9  821.41   306.1  820.07  314.02814.4293
   318.3  813.14   326.5  814.42   330.6  815.29   342.9   821.5   359.3  822.09
   371.5  827.14   387.9  829.19   412.5  837.36     437  840.32   469.7  853.32
     482  859.48   506.6  866.61   531.1  876.69   547.8  880.15   573.9  888.73
#Mann= 6 ,-1,0
       0      .1       0  263.92     .05       0  314.02    .045       0
   326.5     .05       0  363.92     .06       0  473.92      .1       0
Bank Sta=314.02,326.5
XS Rating Curve= 0 ,0
Exp/Cntr(USF)=0,0
Exp/Cntr=0.3,0.1

Type RM Length L Ch R = 1 ,1369    ,36.8,37.1,36.8
BEGIN DESCRIPTION:
Structure 3 XS 1
END DESCRIPTION:
XS GIS Cut Line= 3
1638826.69151854414742.4935166071638686.00883535414820.474929013
1638290.30585753414925.328314613
#Sta/Elev= 30
       0  903.75    12.1  896.96    39.5  886.16    76.1  876.23   112.7  861.88
   121.9  856.51   140.1  843.56   152.7  837.96   175.2  834.56   200.1  828.82
   224.6  820.54   291.1  818.45   299.4  817.02  307.38  812.83   311.8  812.03
   317.3  812.81   328.3  819.23   332.5  820.43   344.9  820.73   353.2  824.17
   365.3  825.58   394.5  835.04   423.5  840.87   464.9  851.07     469  852.58
   481.4   861.3   499.4  865.81   518.7  875.74   543.5  880.46   570.2  889.07
#Mann= 6 ,-1,0
       0      .1       0  240.85     .07       0  307.38    .045       0
   317.3     .07       0  340.85     .06       0  440.85      .1       0
Bank Sta=307.38,317.3
XS Rating Curve= 0 ,0
Exp/Cntr(USF)=0,0
Exp/Cntr=0.3,0.1

Type RM Length L Ch R = 1 ,1332    ,26,26.1,26.2
BEGIN DESCRIPTION:
Structure 2 XS 4
END DESCRIPTION:
XS GIS Cut Line= 3
1638810.88447549 414706.137317581638664.93277794414788.860842903
1638255.00346138414896.348735679
#Sta/Elev= 30
       0  906.83    30.8  892.52    50.7  884.56    81.3  875.54   108.9  865.17
   136.5  849.13   154.9  841.13   168.6  837.47   205.8   830.6   213.8  827.47
   226.5  820.67   292.7  817.78   296.8  817.32  307.81812.3883   313.3  811.41
   317.5  812.39   325.7  818.25   329.9  819.14   345.1  819.36   354.7  823.22
   382.4  827.99   458.1  847.05   474.6  852.21   489.2  861.27   503.6  867.05
   515.4  873.47   524.2  877.22   549.1   881.6   569.7  888.27   591.6  894.19
#Mann= 6 ,-1,0
       0      .1       0  227.76     .07       0  307.81    .045       0
   317.5     .07       0  327.76     .06       0  427.76      .1       0
Bank Sta=307.81,317.5
XS Rating Curve= 0 ,0
Exp/Cntr(USF)=0,0
Exp/Cntr=0.3,0.1

Type RM Length L Ch R = 1 ,1306    ,38.2,38.1,38.2
BEGIN DESCRIPTION:
Structure 2 XS 3
END DESCRIPTION:
XS GIS Cut Line= 3
1638802.45405253414681.8998515621638659.66376359414764.096475449
1638225.49698101414875.799579707
#Sta/Elev= 30
       0  906.13    11.9   899.4    29.3  892.34    82.7  874.91   103.2  865.66
   123.7  858.29   136.5  849.83     155  841.12   171.3  838.12   198.6  828.41
   213.9  824.85   226.2  820.34   292.3  817.86   296.5  817.28     306  812.77
     313  811.32  318.88812.7834   325.4  817.09   329.5  818.26   350.2  818.61
   358.4  821.88   391.5  827.32   458.3  843.31   478.2  850.79   498.8  862.84
   515.4  870.07   527.8  877.36   552.4  881.12   578.7  889.65   613.1  897.53
#Mann= 5 ,-1,0
       0      .1       0  214.76     .07       0     306    .045       0
  318.88     .06       0  424.76      .1       0
Bank Sta=306,318.88
XS Rating Curve= 0 ,0
Exp/Cntr(USF)=0,0
Exp/Cntr=0.3,0.1

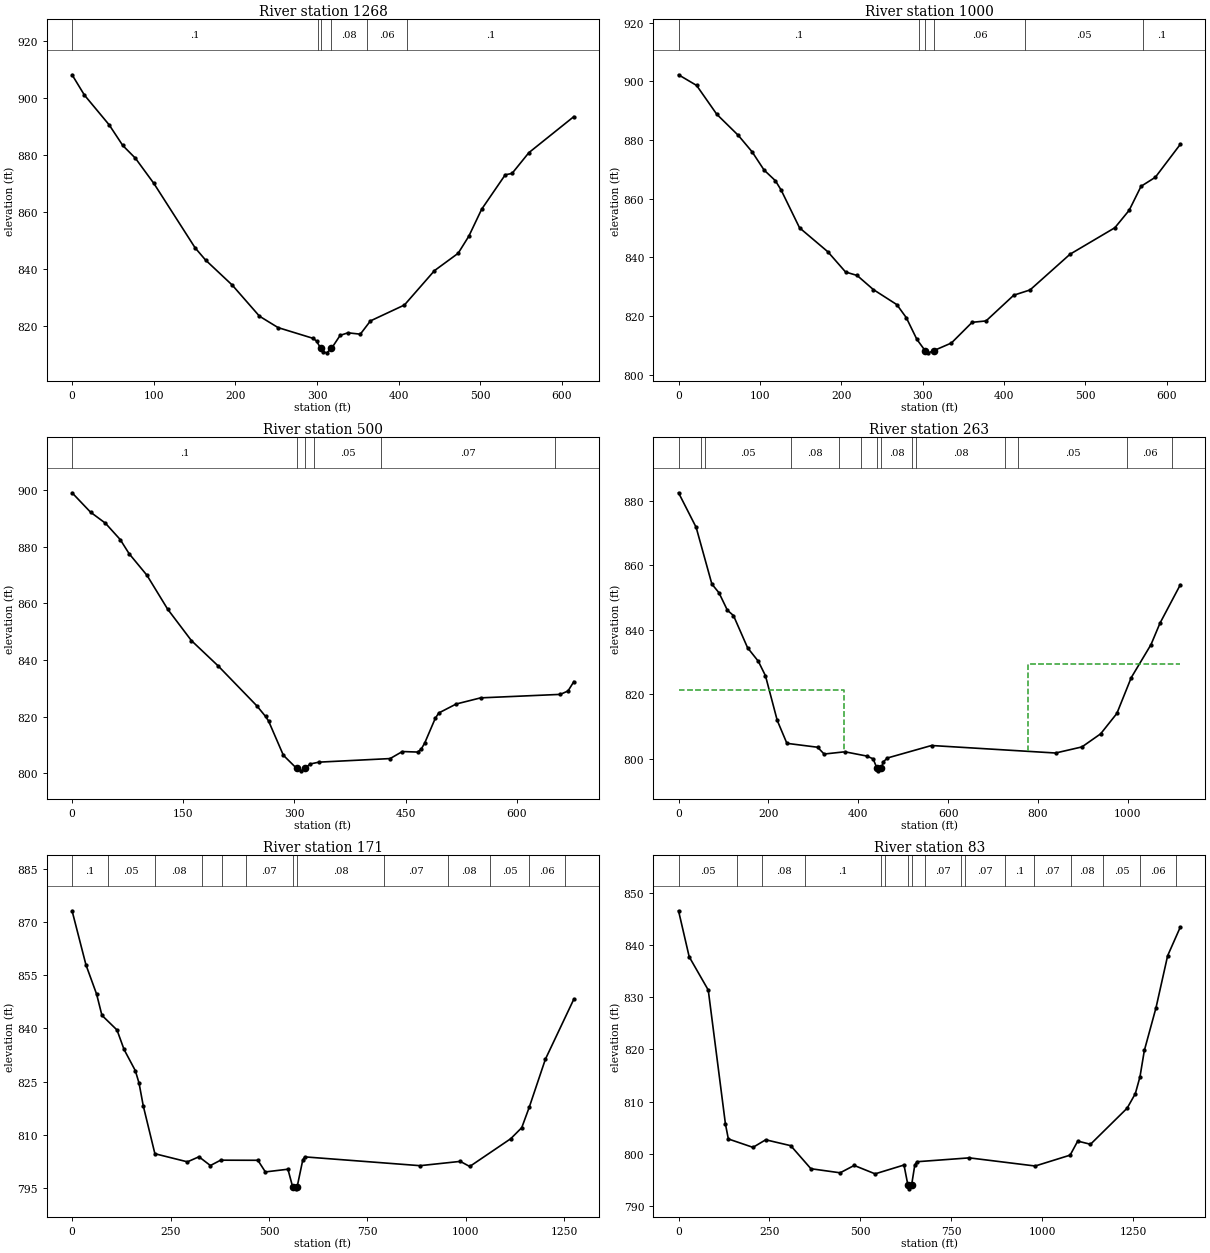
Type RM Length L Ch R = 1 ,1268    ,269.7,268,263.4
BEGIN DESCRIPTION:
Structure 2 XS 2
END DESCRIPTION:
XS GIS Cut Line= 3
1638791.91602382414651.8664697571638660.19066503414725.105769246
1638210.74374082414839.443380679
#Sta/Elev= 30
       0  908.05    15.1  900.95    45.5   890.5    62.1   883.3    77.6  878.83
   100.2  870.01   150.7  847.47   163.5   843.2   196.2  834.43   229.5  823.55
   252.3  819.56   295.3  815.79   299.4  814.85  304.57812.2786   307.6  811.05
   311.8  810.73   317.7  812.28   328.3  816.85   337.9  817.74     353  817.26
   365.4  821.91     407  827.47   443.8   839.5   472.8  845.57   485.9  851.57
   501.6     861   530.5  873.05   538.8  873.52   559.4  880.79   614.5  893.41
#Mann= 6 ,-1,0
       0      .1       0  300.72     .08       0  304.57    .045       0
   317.7     .08       0  360.72     .06       0  410.72      .1       0
Bank Sta=304.57,317.7
XS Rating Curve= 0 ,0
Exp/Cntr(USF)=0,0
Exp/Cntr=0.3,0.1

Type RM Length L Ch R = 1 ,1000    ,497,500,505.2
BEGIN DESCRIPTION:
Structure 2 XS 1
END DESCRIPTION:
XS GIS Cut Line= 6
1638619.74723476414301.6949885931638492.55556001414430.853194833
  1638371.457377414557.1875878421638312.73374118414604.471614003
1638237.64793333414652.7408744251638154.58707584414700.986840919
#Sta/Elev= 30
       0  902.28    22.2  898.65      47  888.82    73.5  881.61    90.5  875.99
   105.2  869.78   119.1  866.15   126.2  862.94   148.8  850.08   183.6  841.91
   205.4  835.01   219.6  833.83   239.5  829.03   268.4  823.89     280  819.46
   293.1  812.02   303.2  808.19   307.3  807.44   313.7808.1757   335.5  810.79
     361  817.85   378.1  818.32   412.2   827.1   432.2  828.89   481.4  841.08
   536.5  850.11   554.1  856.06   568.7  864.24   586.3  867.33     617  878.57
#Mann= 6 ,-1,0
       0      .1       0  296.27     .06       0   303.2    .045       0
   313.7     .06       0  426.27     .05       0  570.93      .1       0
Bank Sta=303.2,313.7
XS Rating Curve= 0 ,0
Exp/Cntr(USF)=0,0
Exp/Cntr=0.3,0.1

Type RM Length L Ch R = 1 ,500     ,238.6,236.7,232.6
BEGIN DESCRIPTION:
Structure XS 4
END DESCRIPTION:
XS GIS Cut Line= 6
1638537.05284634414061.3332645891638442.89325775414063.733850345
1638355.46068984414067.9822014271638280.48019676414069.704967007
1638105.51532359414073.2043038461637897.44201103414203.016695591
#Sta/Elev= 30
       0  898.99    24.9  892.15      45  888.25      65  882.46      77  877.48
     101  869.88     129  857.89     161  846.81   197.1  837.87   249.1  823.83
   261.1  820.02   265.1  818.42   285.1  806.32     303  801.69   309.1  800.83
  314.49801.7233   321.1  803.24   333.1   803.9   429.1  805.16   445.6  807.64
   466.4  807.46   471.1  808.52   475.8  810.66     490  819.35   494.7  821.25
   518.2  824.42   551.2  826.59   658.7  827.82   669.1  829.02     677  832.33
#Mann= 6 ,-1,0
       0      .1       0     303    .045       0  314.49      .1       0
  326.73     .05       0  416.73     .07       0  651.73     .05       0
Bank Sta=303,314.49
XS Rating Curve= 0 ,0
Exp/Cntr(USF)=0,0
Exp/Cntr=0.3,0.1

Type RM Length L Ch R = 1 ,263     ,91.1,91.9,92.2
BEGIN DESCRIPTION:
Structure XS 3
END DESCRIPTION:
XS GIS Cut Line= 6
1638566.03299269413913.8291619641638309.13943783413764.394349007
1638136.19802508413886.9644764891637904.49011285414012.892689655
 1637831.5145211414046.2371583461637820.70008233414309.779399554
#Sta/Elev= 30
       0  882.45    39.2  871.73    74.2  854.14    90.1  851.41   108.7  846.02
   122.3  844.36   153.7  834.37   177.6  830.18   193.5  825.69   219.7  811.84
   241.2  804.72   309.6  803.51   324.1   801.4   370.3   802.1   418.9  800.78
   433.2  799.91   441.8  796.95   444.7  796.19  450.94796.9717   456.1  799.01
   464.8  800.17   563.2  804.05   839.3  801.72     898  803.61   939.6  807.67
   975.7  813.99  1007.7   825.1  1051.7  835.35  1071.8  842.03    1117  853.92
#Mann= 14 ,-1,0
       0     .05       0      50      .1       0      60     .05       0
     250     .08       0   357.2     .06       0  405.19     .08       0
   441.8    .045       0  450.94     .08       0  519.26     .07       0
  529.26     .08       0  726.64     .07       0  756.64     .05       0
  998.85     .06       0 1098.85     .05       0
#XS Ineff= 2 , 0
          368.37  821.38  777.28          829.24
Permanent Ineff=
       F       F
Bank Sta=441.8,450.94
XS Rating Curve= 0 ,0
Exp/Cntr(USF)=0,0
Exp/Cntr=0.3,0.1

Type RM Length L Ch R = 1 ,171     ,87.7,87.9,88.7
BEGIN DESCRIPTION:
Structure XS 2
END DESCRIPTION:
XS GIS Cut Line= 6
1638591.21863532413870.1740480671638295.70709509413680.442206897
1638011.94885475413863.4578766981637790.93842671 413968.77402561
1637793.05249275414065.679479535 1637781.8425815414308.708103059
#Sta/Elev= 30
       0  873.18    35.3  857.92    62.3  849.68    75.8  843.71   114.1  839.57
     132  834.08   160.6  828.11   170.1  824.58   180.7  818.21   210.3  804.69
   292.9   802.4   322.2  803.83   351.2  801.36   377.2  802.87   471.8  802.84
   490.8  799.56   548.1  800.32     560  795.39     568  794.79   571.5  795.37
   585.9  802.98   590.9   803.8   883.5  801.32   985.7  802.53  1009.7  801.09
  1113.8  808.92  1141.8  812.04  1160.8  817.79  1201.8  831.33  1274.1  848.28
#Mann= 13 ,-1,0
       0      .1       0      90     .05       0     210     .08       0
     330      .1       0  381.18     .08       0  441.18     .07       0
     560    .045       0   571.5     .08       0  791.66     .07       0
  953.88     .08       0  1060.8     .05       0  1160.8     .06       0
  1250.8     .05       0
Bank Sta=560,571.5
XS Rating Curve= 0 ,0
Exp/Cntr(USF)=0,0
Exp/Cntr=0.3,0.1

Type RM Length L Ch R = 1 ,83      ,,,
BEGIN DESCRIPTION:
Structure 1 XS 1
END DESCRIPTION:
XS GIS Cut Line= 4
1638605.23402501 413776.146257481638319.79674184413596.488673363
1637767.06975058413877.6892970031637767.50731601414299.464235617
#Sta/Elev= 30
       0  846.54    29.3  837.73    81.7  831.36   128.9  805.72   136.9  802.86
   204.6  801.25   239.6   802.7   308.5  801.57   363.8  797.16   444.2  796.38
   482.8  797.79   540.3  796.18   619.7  797.87  630.48 794.006   633.1  793.31
   640.5  793.99   649.4  797.88   655.4   798.5   799.2  799.24   980.3  797.68
  1076.3  799.76  1097.2  802.45  1132.3  801.84    1233  808.75  1255.5  811.53
  1268.3  814.76  1280.3   819.8  1312.3  827.96  1344.3  837.93  1379.2  843.43
#Mann= 17 ,-1,0
       0     .05       0     160     .07       0     230     .08       0
  347.27      .1       0  557.27     .07       0  567.27     .08       0
  630.48    .045       0   640.5     .08       0  677.27     .07       0
  777.27     .08       0  787.27     .07       0  897.27      .1       0
  977.42     .07       0 1077.42     .08       0 1167.42     .05       0
 1267.42     .06       0 1367.42     .05       0
Bank Sta=630.48,640.5
XS Rating Curve= 0 ,0
Exp/Cntr(USF)=0,0
Exp/Cntr=0.3,0.1
LCMann Table=0

Chan Stop Cuts=-1
Use User Specified Reach Order=0
Composite Channel Slope=5